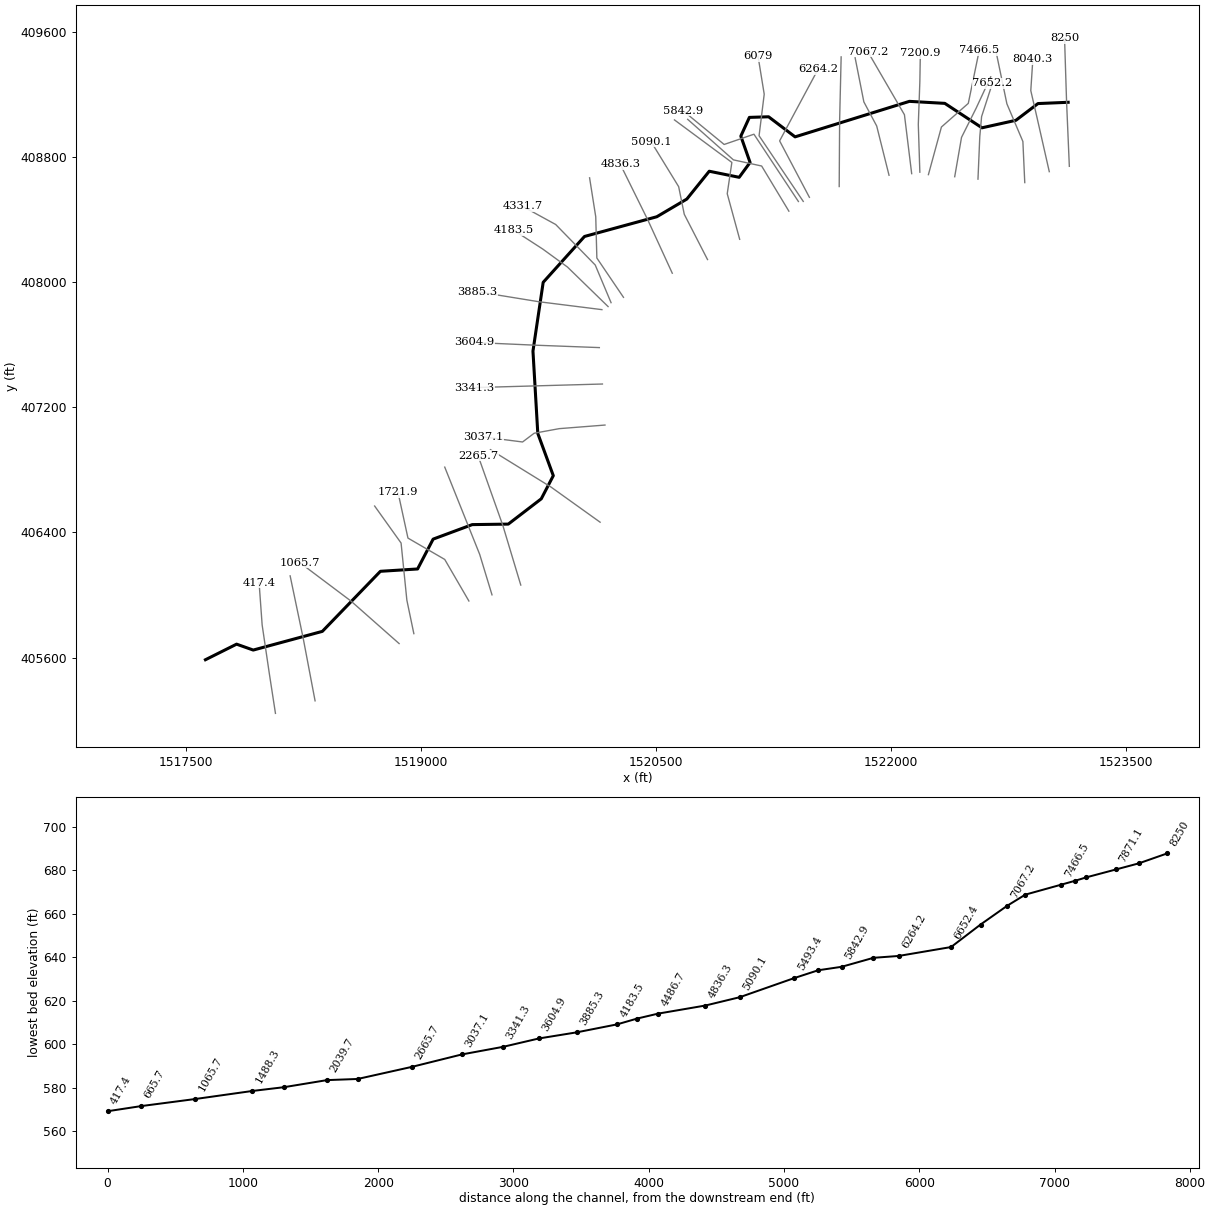
--- PADDLECR.prj (project) ---

Proj Title=PADDLECR
Current Plan=p01
Default Exp/Contr=0,0
English Units
Geom File=g01
Flow File=f01
Plan File=p01
BEGIN DESCRIPTION:
END DESCRIPTION:
DSS Export Rating Curves= 0
DSS Export Rating Curve Sorted= 0
DSS Export Volume Flow Curves= 0
DXF OffsetX= 0
DXF OffsetY= 0
DXF ScaleX= 0
DXF ScaleY= 0

--- PADDLECR.p01 (plan) ---

Plan Title=Floodplain
Program Version=4.00
Geom File=g01
Flow File=f01
K Sum by GR=0
Std Step Tol=0.01
Critical Tol=0.01
Num of Std Step Trials=20
Max Error Tol=0.3
Flow Tol Ratio=0.001
Split Flow NTrial=30
Split Flow Tol=0.02
Split Flow Ratio=0.02
Log Output Level=0
Friction Slope Method=1
Unsteady Friction Slope Method=2
Unsteady Bridges Friction Slope Method=1
Global Log Level=0
CheckData=False
Run HTab=0
Run UNet=0
Run PostProcess=0
UNET Theta=0
UNET Theta Warmup=0
UNET ZTol=0
UNET ZSATol=0
UNET MxIter=0
UNET MaxInSteps=0
UNET DtIC=0
UNET DtMin=0
UNET MaxCRTS=0
UNET WFStab=0
UNET SFStab=0
UNET WFX=0
UNET SFX=0
UNET DSS MLevel=0
UNET DZMax Abort=0
UNET Convert EG Bridges=0
UNET Use Existing IB Tables=0
UNET Froude Limit=0
UNET Froude Power=0
Write IC File=0
Echo Input=False
Echo Output=False
Write Detailed=0

--- PADDLECR.f01 (steady flow) ---

Flow Title=NFF Regression Equation
Program Version=4.00
Number of Profiles=1
Profile Names=P100yr
River Rch & RM=PADDLECR,Main      ,8250
     363
River Rch & RM=PADDLECR,Main      ,6870.4
     389
River Rch & RM=PADDLECR,Main      ,4486.7
     430
River Rch & RM=PADDLECR,Main      ,4183.5
     498
River Rch & RM=PADDLECR,Main      ,3885.3
     512
Boundary for River Rch & Prof#=PADDLECR,Main      ,1
Up Type=0
Dn Type=3
Dn Slope=0.008828

--- PADDLECR.g01 (geometry) ---

Geom Title=USGS 10m DEM
Program Version=4.00

River Reach=PADDLECR        ,Main
Reach XY= 30
     1523132.662      409150.954     1522939.871       409142.82
      1522798.97       409035.83     1522582.359      408987.802
     1522344.902        409144.1      1522118.89      409156.919
     1521388.745      408929.889     1521219.613      409058.311
     1521096.894      409054.363     1521042.246      408934.603
     1521101.331      408766.247       1521031.7      408671.217
     1520840.562       408710.08     1520697.397      408532.135
     1520505.732       408419.05     1520043.956      408292.925
     1519780.081      407999.672     1519714.839      407559.788
     1519745.728      407033.361     1519844.706      406763.247
     1519767.878      406615.328     1519557.238      406453.604
     1519327.073      406450.338     1519077.308      406357.534
     1518978.043      406166.709     1518740.588      406151.787
     1518369.831      405767.673     1517928.565      405648.137
     1517822.056      405685.896     1517623.204      405586.262

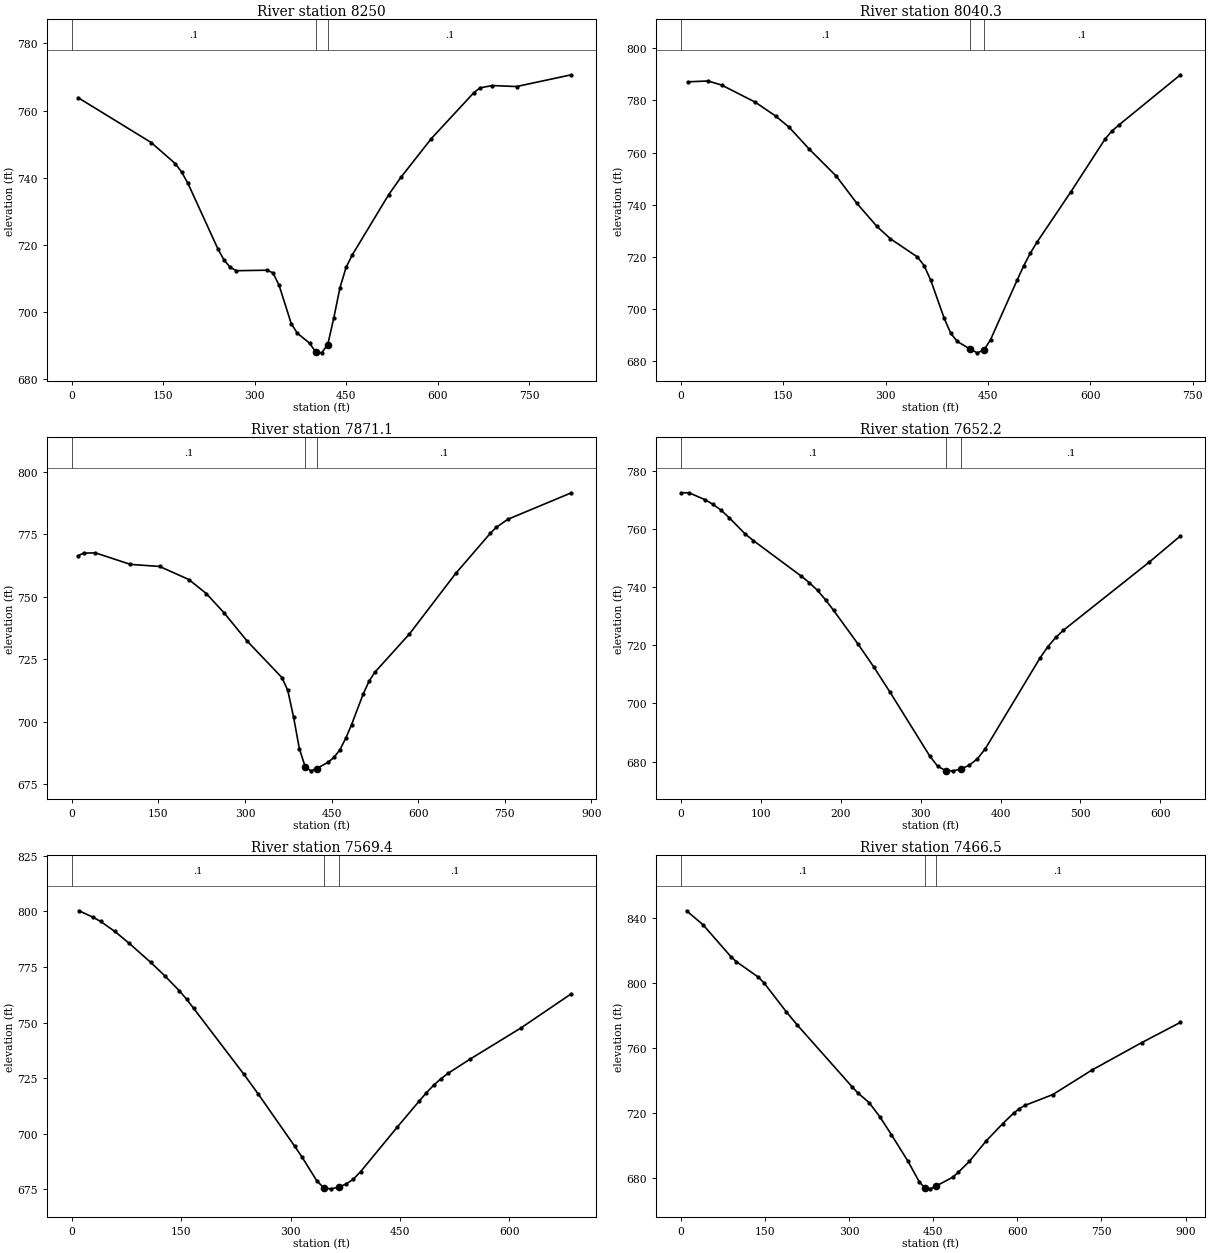
Type RM Length L Ch R = 1 ,8250    ,205,209.7,214.6
XS GIS Cut Line= 3
     1523140.191      408741.481     1523122.667      409150.636
     1523109.632      409559.923
#Sta/Elev= 30
      10  763.84   129.9  750.48   169.8  744.14   179.8  741.69   189.8  738.47
   239.7  718.66   249.7  715.41   259.7  713.28   269.7   712.3   319.6  712.45
   329.6  711.68   339.6     708   359.6  696.55   369.6  693.69   389.6  690.73
   399.5  688.17   409.5  687.84   419.5  690.31   429.5  698.33   439.5  707.23
   449.5  713.27   459.5  716.95   519.4  734.95   539.4   740.1   589.3  751.64
   659.2  765.35   669.2  766.76   689.2  767.44   729.1  767.15     819  770.65
#Mann= 3 , 0 , 0
       0      .1       0   399.5    .045       0   419.5      .1       0
Bank Sta=399.5,419.5
XS Rating Curve= 0 ,0
Exp/Cntr=0.3,0.1

Type RM Length L Ch R = 1 ,8040.3  ,165.7,169.3,172.8
XS GIS Cut Line= 4
     1523012.093      408707.372      1522933.37      409055.062
     1522894.009      409225.627     1522907.129      409425.713
#Sta/Elev= 30
     9.9  787.14    39.6  787.46    59.4  785.92   108.9  779.33   138.6  774.04
   158.4  769.76   188.1  761.32   227.8  750.93   257.5  740.66   287.2  731.71
     307  726.98   346.6     720   356.5  716.65   366.2  710.99   385.7  696.57
   395.4  690.74   405.1  687.61   424.3   684.6   434.3  683.26   444.3   684.4
   453.7  688.29   492.6  711.09   502.4  716.65   512.1   721.5   521.8  725.67
   571.6  745.03   621.8  765.28   631.8  768.32   641.8  770.58   732.1  789.84
#Mann= 3 , 0 , 0
       0      .1       0   424.3    .045       0   444.3      .1       0
Bank Sta=424.3,444.3
XS Rating Curve= 0 ,0
Exp/Cntr=0.3,0.1

Type RM Length L Ch R = 1 ,7871.1  ,231.2,218.9,206.5
XS GIS Cut Line= 4
     1522855.517      408637.337     1522843.519      408900.427
     1522741.414      409141.104     1522672.136      409474.821
#Sta/Elev= 30
    10.1  766.39    20.3  767.47    40.5  767.58   101.3  762.97   151.9  762.14
   202.6  756.92     233  751.28   263.4  743.66   303.6  732.32   363.9  717.73
     374  712.66     384  702.03   394.1  689.36   404.2  682.07   414.2  680.44
   424.2  681.36   444.4  683.92   454.4  685.88   464.5   688.9   474.5  693.44
   484.6  698.89   504.7  711.11   514.7  716.16   524.8  719.81     585  735.18
   665.1  759.34   725.3  775.45   735.3  777.75   755.4  780.98   865.6  791.59
#Mann= 3 , 0 , 0
       0      .1       0   404.2    .045       0   424.2      .1       0
Bank Sta=404.2,424.2
XS Rating Curve= 0 ,0
Exp/Cntr=0.3,0.1

Type RM Length L Ch R = 1 ,7652.2  ,92.2,82.8,73.4
XS GIS Cut Line= 4
     1522556.771      408659.505      1522568.31      408930.674
     1522579.849      409059.528     1522649.084      409273.001
#Sta/Elev= 30
       0  772.42    10.1  772.42    30.2  770.02    40.2  768.42    50.3   766.4
    60.3  763.84    80.4  758.24    90.5     756   150.8  743.71   160.8  741.46
   170.9  738.85   180.9  735.63     191  731.99   221.2  720.56   241.3  712.54
   261.4  703.96   311.2  681.97   321.2  678.43   331.1  676.89   341.1  676.81
   351.1  677.53     361  678.76   370.9  680.92   380.9  684.39   449.6   715.7
   459.3  719.53   469.1  722.67   478.8  725.17   586.2  748.59   625.2  757.59
#Mann= 3 , 0 , 0
       0      .1       0   331.1    .045       0   351.1      .1       0
Bank Sta=331.1,351.1
XS Rating Curve= 0 ,0
Exp/Cntr=0.3,0.1

Type RM Length L Ch R = 1 ,7569.4  ,112.5,102.8,93.2
XS GIS Cut Line= 4
     1522408.124       408674.92     1522451.679      408926.577
     1522546.051      409115.319     1522638.002       409313.74
#Sta/Elev= 30
     9.8  800.27    29.5  797.26    39.3  795.47    58.9  790.96    78.6  785.61
   108.1  777.06   127.7  770.91   147.3  764.29   157.2  760.52     167  756.38
   235.8  726.78   255.4  717.93   305.6  694.36   315.7  689.46   335.8   678.9
   345.9   675.5   355.9  675.23   365.9  676.05     376  677.36     386  679.58
   396.1  683.01   446.3  703.01   476.4  714.72   486.3  718.45   496.2  721.84
   506.2  724.75   516.1   727.2   545.9  733.51   615.5  747.49   685.1  762.97
#Mann= 3 , 0 , 0
       0      .1       0   345.9    .045       0   365.9      .1       0
Bank Sta=345.9,365.9
XS Rating Curve= 0 ,0
Exp/Cntr=0.3,0.1

Type RM Length L Ch R = 1 ,7466.5  ,245,265.6,286.2
XS GIS Cut Line= 4
     1522240.181      408688.299     1522323.272       408992.74
     1522494.902      409144.021     1522565.045      409483.414
#Sta/Elev= 30
     9.9  844.23    39.4   835.6    88.8  816.11    98.6  813.01   138.1  803.44
   147.9  800.01   187.4  782.35   207.1  774.19   305.7  735.92   315.6  732.29
   335.5  726.44   355.4  717.34   375.3   706.7   405.1  690.25     425  677.72
   434.9  674.02   444.9  673.44   454.9  675.13   484.7  680.56   494.6  683.59
   514.5  690.34   544.4  702.88   574.1  713.57   593.9  720.13   603.8  722.76
   613.7  724.72   663.2  731.33   732.5  746.29   821.6  763.22   890.9  775.69
#Mann= 3 , 0 , 0
       0      .1       0   434.9    .045       0   454.9      .1       0
Bank Sta=434.9,454.9
XS Rating Curve= 0 ,0
Exp/Cntr=0.3,0.1

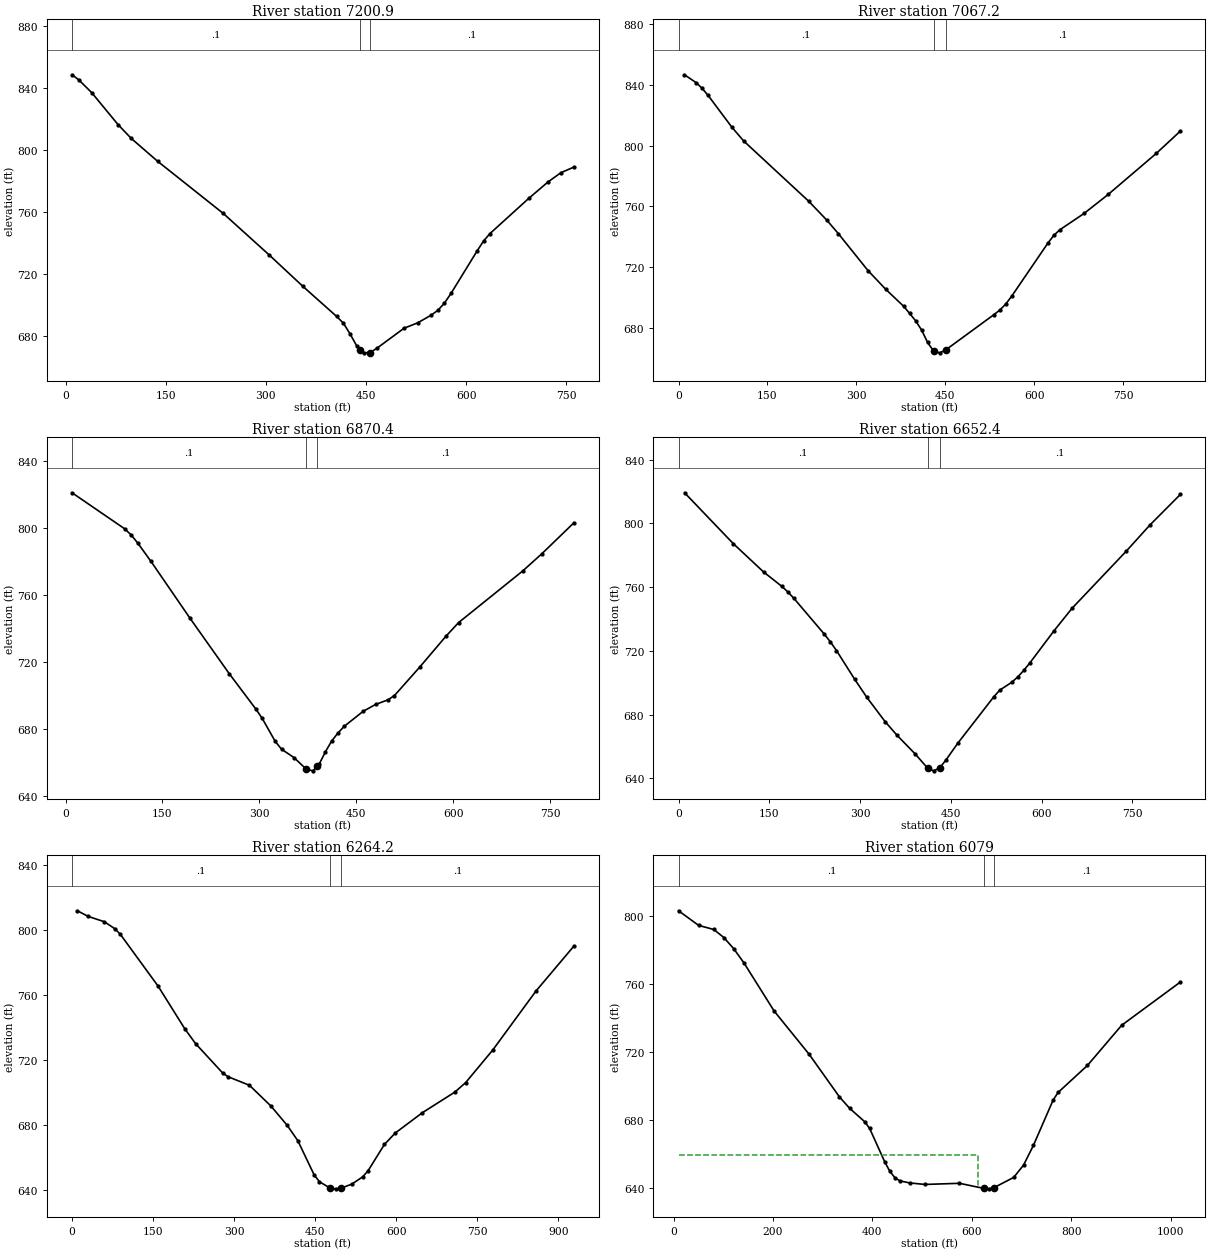
Type RM Length L Ch R = 1 ,7200.9  ,119.7,133.7,147.9
XS GIS Cut Line= 4
     1522185.507      408704.092     1522175.667      409009.141
     1522185.507      409281.389     1522188.788      409465.075
#Sta/Elev= 30
     9.8  848.42    19.7  845.21    39.4   836.8    78.8  816.18    98.5   807.3
   137.8   792.6   236.3  758.85   305.2  731.99   355.7  711.69   406.1  692.33
   416.2  687.98   426.3  680.94   436.4  673.09  441.41  670.93   446.5  668.84
   456.5  669.05   466.6   671.9     507  684.73   527.2  688.17   547.4  693.13
   557.5  696.25   567.5  700.96   577.6  707.41   616.3  734.58     626  741.01
   635.6  745.85   693.7  768.58   722.7  779.24     742  785.21   761.3  788.79
#Mann= 3 , 0 , 0
     9.8      .1       0  441.41    .045       0   456.5      .1       0
Bank Sta=441.41,456.5
XS Rating Curve= 0 ,0
Exp/Cntr=0.3,0.1

Type RM Length L Ch R = 1 ,7067.2  ,197.6,196.8,195.8
XS GIS Cut Line= 3
     1522133.323      408694.598     1522087.105      409071.463
     1521852.683      409475.527
#Sta/Elev= 30
      10  846.57      30  841.33      40  837.57      50  832.95    89.9  812.15
   109.9  803.06   219.8  763.36   249.8  751.16   269.8  742.07   319.7  717.83
   349.7  705.49   379.7  694.41   389.8  689.73     400  684.84   410.2  678.71
   420.3  670.57   430.6  664.78   440.6  663.72   450.6  665.55     532  688.77
   542.2  691.85   552.3  695.84   562.5  701.14   623.4  735.93   633.6  741.09
   643.7   744.7   684.3  755.36     725  767.85   806.2  794.85   846.8  809.52
#Mann= 3 , 0 , 0
       0      .1       0   430.6    .045       0   450.6      .1       0
Bank Sta=430.6,450.6
XS Rating Curve= 0 ,0
Exp/Cntr=0.3,0.1

Type RM Length L Ch R = 1 ,6870.4  ,230.6,218,205
XS GIS Cut Line= 4
     1521988.701      408684.411     1521909.979        408999.3
     1521827.977      409153.465     1521772.215      409435.554
#Sta/Elev= 30
    10.1  821.28    91.3   799.8   101.4  796.14   111.6  791.31   131.9  780.45
   192.7  746.25   253.6  713.02   294.2  692.19   304.3  686.47   324.6  672.62
   334.3  668.02   353.7  662.96   372.8  655.99   382.8  655.08  389.43  657.71
   392.5  659.03   402.2  666.45   411.9  672.94   421.6  677.68   431.3  681.69
   460.4  690.59   479.8  694.76   499.2  697.54   509.1   700.1   548.8  717.37
   588.4  735.39   608.3  743.69   707.4   774.5   737.2  784.84   786.7  803.32
#Mann= 3 , 0 , 0
    10.1      .1       0   372.8    .045       0  389.43      .1       0
Bank Sta=372.8,389.43
XS Rating Curve= 0 ,0
Exp/Cntr=0.3,0.1

Type RM Length L Ch R = 1 ,6652.4  ,399.9,388.2,376.9
XS GIS Cut Line= 3
     1521670.532      408612.249     1521673.212      409033.782
     1521682.927      409441.245
#Sta/Elev= 30
      10  819.25    90.3  787.39   140.5  769.56   170.6  760.53   180.7  756.99
   190.7  752.94   240.9  730.51   250.9  725.64     261   720.2   291.1  702.15
   311.1  690.85   341.2  675.67   361.3  666.91   391.4  655.15   411.5  646.43
   421.5  644.71   431.5  646.55   441.4  651.28   461.3  661.99     521  691.24
   530.9  695.41   550.8  700.35   560.7  703.73   570.7  707.89   580.6   712.5
   620.4  732.62   650.2  746.74   739.7  782.57   779.4  799.23   829.1  818.18
#Mann= 3 , 0 , 0
       0      .1       0   411.5    .045       0   431.5      .1       0
Bank Sta=411.5,431.5
XS Rating Curve= 0 ,0
Exp/Cntr=0.3,0.1

Type RM Length L Ch R = 1 ,6264.2  ,176.7,185.2,193.7
XS GIS Cut Line= 3
     1521480.184      408543.297      1521290.04      408904.178
     1521536.048      409363.392
#Sta/Elev= 30
     9.9  811.66    29.8   808.2    59.7  804.93    79.6  800.52    89.5  797.11
   159.2  765.33   208.9  738.94   228.8  729.87   278.6  711.94   288.5  709.61
   328.3  704.31   368.1  691.56     398  679.76   417.9  670.23     448  649.27
     458  644.92   478.1  641.02   488.1   640.6   498.1  641.02   518.1  643.54
   538.1  648.01   548.2  651.85   578.2  667.92   598.3  674.95   648.4  687.42
   708.5   700.1   728.5  705.92   778.6  725.93   858.7  762.27   928.9  789.91
#Mann= 3 , 0 , 0
       0      .1       0   478.1    .045       0   498.1      .1       0
Bank Sta=478.1,498.1
XS Rating Curve= 0 ,0
Exp/Cntr=0.3,0.1

Type RM Length L Ch R = 1 ,6079    ,184.8,236.1,287.4
XS GIS Cut Line= 4
     1521440.925      408517.126     1521158.836      408936.979
     1521191.637      409202.667     1521152.276      409445.394
#Sta/Elev= 30
    10.1   802.9    50.6  794.32    80.9  791.93   101.2  787.22   121.4  780.54
   141.6  772.36   202.3  744.11   273.1  718.59   333.8  693.67   354.1  687.05
   384.4  679.17   394.5  675.17   424.9  655.55     435  650.09   445.1  646.35
   455.2  644.42   475.5   643.2   505.8  642.33   575.2     643   624.7  639.97
   634.7  639.75   644.7  640.47   684.3  646.47   704.1   653.7   723.9  665.24
   763.6  691.86   773.5  696.29   832.5  712.13   901.4  735.72  1019.4  761.07
#Mann= 3 , 0 , 0
    10.1      .1       0   624.7    .045       0   644.7      .1       0
#XS Ineff= 2 , 0
          613.15  659.72
Permanent Ineff=
       F       F
Bank Sta=624.7,644.7
XS Rating Curve= 0 ,0
Exp/Cntr=0.3,0.1

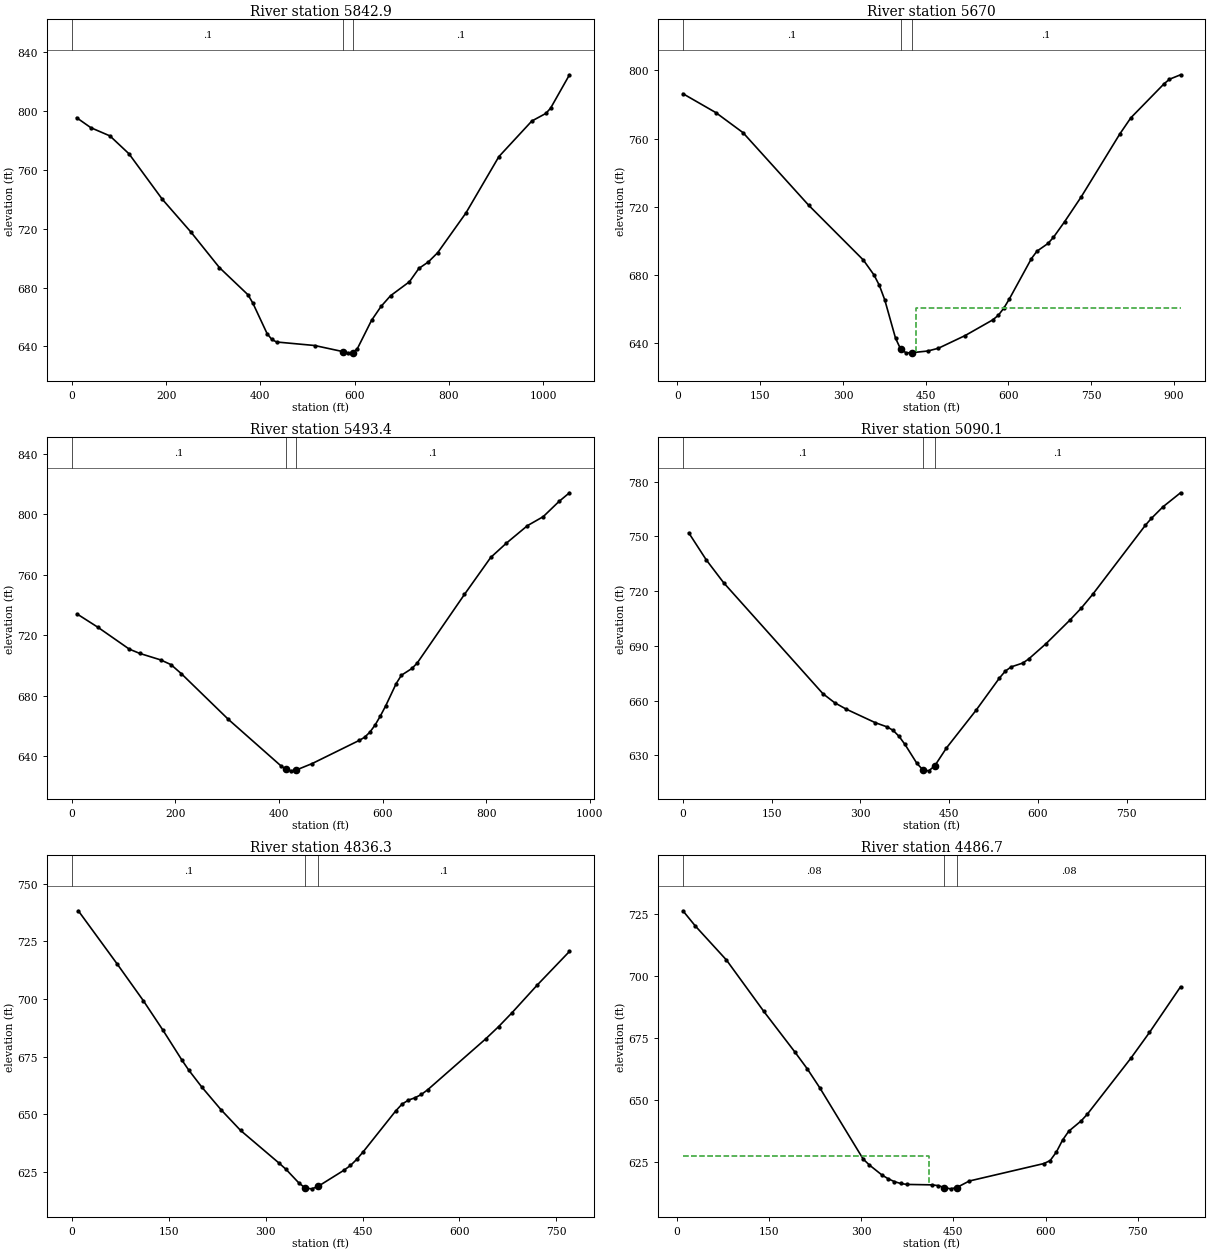
Type RM Length L Ch R = 1 ,5842.9  ,186.7,172.9,159.1
XS GIS Cut Line= 4
     1521409.893      408516.744     1521126.035      408946.819
      1520935.79      408881.217     1520673.489      409096.772
#Sta/Elev= 30
    10.1  795.62    40.4   788.8    80.8  783.23   121.2  771.07     192  740.09
   252.6  717.83   313.2   693.6   373.8  675.11     384  669.51   414.3  648.72
   424.4  644.68   434.5  642.98   515.3  640.59   575.7   636.4   585.7   635.6
   595.7  635.61   605.9  638.42     636   657.7   656.2  667.19   676.3  674.45
   716.5     684   736.5  693.05   756.5  697.44   776.5   703.8   836.4  730.81
   906.3  769.14   976.2  793.36  1006.1  798.55  1016.1  802.15  1056.1  824.83
#Mann= 3 , 0 , 0
       0      .1       0   575.7    .045       0   595.7      .1       0
Bank Sta=575.7,595.7
XS Rating Curve= 0 ,0
Exp/Cntr=0.3,0.1

Type RM Length L Ch R = 1 ,5670    ,214.7,176.6,138.5
XS GIS Cut Line= 4
     1521349.082      408454.804     1521175.237      408743.453
     1520994.831      408782.814     1520702.902      409041.942
#Sta/Elev= 30
     9.9  786.35    69.4  775.27   118.9  763.44   237.9  720.77     337  688.57
   356.4  679.75   366.1   673.6   375.8  665.15   395.3  642.66   404.7  636.12
   414.7  634.01   424.7  634.09   453.6  635.08     473   636.7   521.6  644.18
   571.7  653.41   581.7  656.09   591.7  660.29   601.7  665.71   641.7  689.41
   651.7  693.77   671.7  698.29   681.7  701.96   701.8  711.08   731.8  725.62
   801.9  762.67   821.9  772.17   881.9  792.09   891.9  794.84     912  797.47
#Mann= 3 , 0 , 0
     9.9      .1       0   404.7    .045       0   424.7      .1       0
#XS Ineff= 2 , 0
                          432.03          660.53
Permanent Ineff=
       F       F
Bank Sta=404.7,424.7
XS Rating Curve= 0 ,0
Exp/Cntr=0.3,0.1

Type RM Length L Ch R = 1 ,5493.4  ,394.6,403.3,412
XS GIS Cut Line= 4
     1521034.977       408274.75      1520955.47      408566.327
     1520984.991      408766.413     1520618.427      409038.266
#Sta/Elev= 30
    10.1  734.08    50.4  725.28   110.8  710.87     131  708.03   171.3  703.75
   191.4  700.61   211.6  694.56   302.2  664.42   403.3  633.83   413.6  631.33
   423.6  630.42   433.6  631.01     464  635.23   555.2  650.59   565.3  652.62
   575.5  656.02   585.6  660.75   595.7   666.7   605.9  673.33   626.2  688.09
   636.3   693.6   656.6  698.07   666.7  701.62     758     747   808.7  771.43
   839.1  780.93   879.7  792.47   910.1   798.4   940.6  808.45   960.8  814.18
#Mann= 3 , 0 , 0
       0      .1       0   413.6    .045       0   433.6      .1       0
Bank Sta=413.6,433.6
XS Rating Curve= 0 ,0
Exp/Cntr=0.3,0.1

Type RM Length L Ch R = 1 ,5090.1  ,248,253.8,260.2
XS GIS Cut Line= 4
      1520829.58      408145.302     1520681.051      408434.799
     1520645.286       408611.37     1520470.015      408897.617
#Sta/Elev= 30
     9.9  751.89    39.4  737.14      69  724.54   236.6  663.86   256.4  658.92
   276.1  655.37   325.4  647.94   345.4  645.64   355.4  643.74   365.4  640.47
   375.4  636.05   395.4  625.75   405.5  622.18   415.5   621.6   425.5  624.24
   445.5  634.12   495.5  654.75   535.1  672.43     545   676.2   554.9  678.51
   574.6  680.63   584.5  682.84   614.1  691.31   653.6  703.95   673.4  710.71
   693.1   718.4   781.9  756.12   791.8  759.79   811.6  766.19   841.2  773.85
#Mann= 3 , 0 , 0
       0      .1       0   405.5    .045       0   425.5      .1       0
Bank Sta=405.5,425.5
XS Rating Curve= 0 ,0
Exp/Cntr=0.3,0.1

Type RM Length L Ch R = 1 ,4836.3  ,359.7,349.6,339
XS GIS Cut Line= 3
       1520604.5      408057.912     1520449.622      408395.615
     1520273.209      408753.293
#Sta/Elev= 30
      10   738.2    70.3   715.1   110.5  699.32   140.6  686.66   170.7  673.39
   180.7  669.29   200.8  661.97   230.9  652.03   261.1  643.09   321.3  628.78
   331.4  626.25   351.4  620.32   361.5  618.08   371.5  617.77   381.5   618.9
   421.4  625.86   431.3   627.9   441.3  630.63   451.3  633.92   501.1  651.44
   511.1  654.46   521.1  656.21   531.1   657.2     541  658.64     551  660.73
   640.7  682.74   660.7  688.06   680.6  693.82   720.5  706.07   770.3   720.6
#Mann= 3 , 0 , 0
       0      .1       0   361.5    .045       0   381.5      .1       0
Bank Sta=361.5,381.5
XS Rating Curve= 0 ,0
Exp/Cntr=0.3,0.1

Type RM Length L Ch R = 1 ,4486.7  ,136.3,155,173.7
XS GIS Cut Line= 4
      1520292.89      407903.747     1520122.885      408155.045
     1520115.765      408418.723     1520076.403       408668.01
#Sta/Elev= 30
    10.1  726.41    30.3  720.26    80.9  706.52   141.6  685.78   192.2  669.35
   212.4  662.54   232.6  654.93   303.4  626.05   313.5  623.66   333.8  619.64
     344  618.12   354.1  616.96   364.3  616.21   374.4  615.82     415  615.65
   425.1  615.35   435.4  614.57   445.4  614.04   455.4  614.54   475.9   617.2
   597.5  624.27   607.6  625.49   617.7  628.95   627.7  633.74   637.8  637.34
     658  641.51   668.1  644.25   738.8  666.83   769.1  677.25   819.6  695.69
#Mann= 3 , 0 , 0
    10.1     .08       0   435.4    .045       0   455.4     .08       0
#XS Ineff= 2 , 0
          410.71  627.27
Permanent Ineff=
       F       F
Bank Sta=435.4,455.4
XS Rating Curve= 0 ,0
Exp/Cntr=0.3,0.1

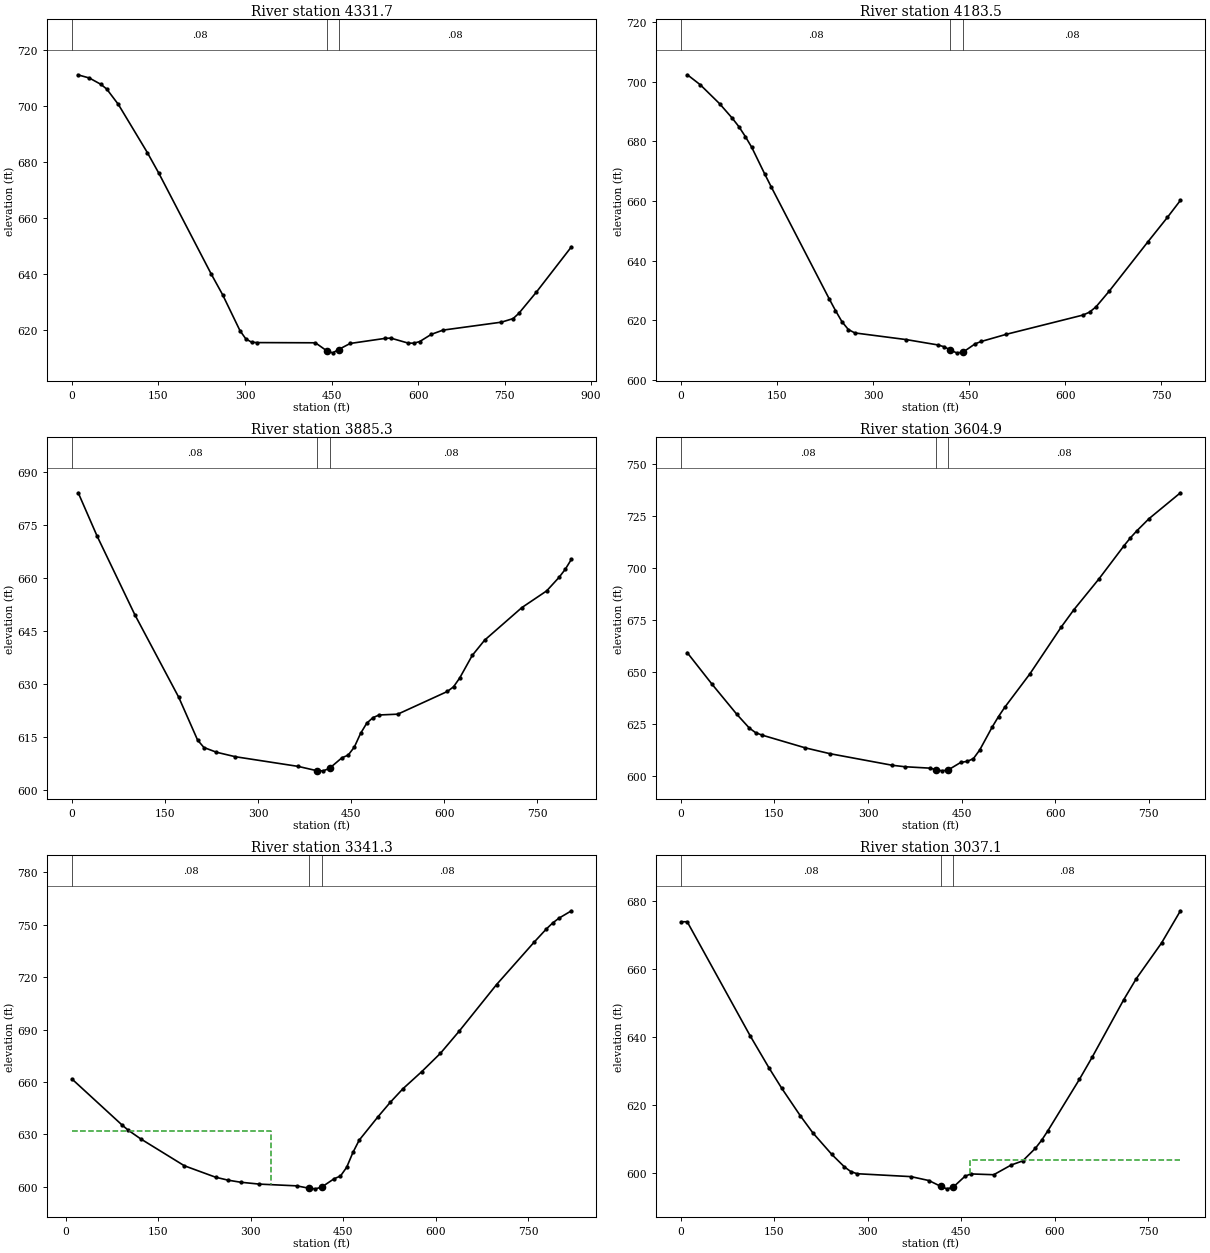
Type RM Length L Ch R = 1 ,4331.7  ,144,148.2,152.4
XS GIS Cut Line= 4
     1520213.542      407869.603     1520112.485      408110.394
     1519859.917      408369.521     1519646.844      408486.217
#Sta/Elev= 30
      10  711.11    30.1  709.96    50.2  707.69    60.3  706.01    80.4  700.53
   130.6  683.34   150.7   675.9     241  640.08   261.1  632.55   291.3  619.67
   301.3  616.78   311.4  615.55   321.4  615.42     422  615.35   442.1  612.43
   452.1  611.76   462.1  612.94   482.3  615.11   542.6  616.92   552.6  617.03
   582.8  615.24   592.8  615.21   602.9   615.8     623  618.37   643.2  619.88
   744.5  622.72   764.7  623.99   774.8   625.9   805.2  633.49   865.9  649.66
#Mann= 3 , 0 , 0
       0     .08       0   442.1    .045       0   462.1     .08       0
Bank Sta=442.1,462.1
XS Rating Curve= 0 ,0
Exp/Cntr=0.3,0.1

Type RM Length L Ch R = 1 ,4183.5  ,285.6,298.2,310
XS GIS Cut Line= 4
     1520194.487      407844.705     1519935.359      408097.273
     1519777.914      408212.077     1519590.949       408333.44
#Sta/Elev= 30
    10.1  702.38    30.2  699.03    60.3  692.69    80.4  687.75    90.5  684.96
   100.5  681.67   110.6  678.01   130.7  669.13   140.7  664.87   231.2   627.3
   241.2  623.29   251.3  619.54   261.3  616.91   271.4  615.77   351.8  613.53
   400.8  611.75   410.6  611.14   420.1  610.09   430.1  609.09   440.1  609.29
   459.3  612.13     469  612.92     508  615.32   627.6  621.77   637.8  622.75
   647.9  624.54   668.2  629.72     729  646.39   759.3  654.55   779.6  660.25
#Mann= 3 , 0 , 0
       0     .08       0   420.1    .045       0   440.1     .08       0
Bank Sta=420.1,440.1
XS Rating Curve= 0 ,0
Exp/Cntr=0.3,0.1

Type RM Length L Ch R = 1 ,3885.3  ,278.3,280.4,283.3
XS GIS Cut Line= 3
     1520155.126      407825.025     1519753.027      407875.556
     1519358.062      407939.828
#Sta/Elev= 30
    10.1  684.18    40.5  671.93   101.3  649.67   172.2  626.25   202.6  614.13
   212.8  612.03     233  610.69   263.4  609.42   364.7  606.68   395.3  605.44
   405.3  605.42   415.3  606.14   435.3  609.12   445.3  609.86   455.3  612.15
   465.3     616   475.3  618.91   485.3  620.49   495.3  621.24   525.3  621.47
   605.3   627.9   615.3  629.23   625.3  631.75   645.4  638.11   665.4  642.44
   725.4  651.66   765.4  656.39   785.4  660.23   795.4  662.51   805.4  665.37
#Mann= 3 , 0 , 0
       0     .08       0   395.3    .045       0   415.3     .08       0
Bank Sta=395.3,415.3
XS Rating Curve= 0 ,0
Exp/Cntr=0.3,0.1

Type RM Length L Ch R = 1 ,3604.9  ,261.9,263.6,265.4
XS GIS Cut Line= 3
     1520138.725      407582.298     1519730.339      407597.683
     1519338.381      407615.099
#Sta/Elev= 30
      10  659.45    49.8  644.26    89.7  629.74   109.6  623.18   119.6  620.97
   129.6  619.81   199.4  613.64   239.2  610.82   338.9  605.27   358.8  604.57
   398.7  603.89   408.7  603.21   418.7  602.59   428.7  603.05   448.9  606.67
     459  607.13     469  608.46   479.1   612.6   499.2  623.68   509.3   628.7
   519.3  633.15   559.6  649.21   609.9  671.74     630  679.99   670.2   694.8
   710.5  710.79   720.5  714.49   730.6  717.82   750.7  723.83     801  736.25
#Mann= 3 , 0 , 0
       0     .08       0   408.7    .045       0   428.7     .08       0
Bank Sta=408.7,428.7
XS Rating Curve= 0 ,0
Exp/Cntr=0.3,0.1

Type RM Length L Ch R = 1 ,3341.3  ,300.3,304.3,309.4
XS GIS Cut Line= 2
     1520158.406       407349.41     1519338.381       407326.45
#Sta/Elev= 30
    10.1  661.68    91.1  635.41   101.3  632.37   121.5   627.4   192.4  611.97
   243.1  605.41   263.3  603.72   283.6  602.54     314  601.46   374.7  600.46
   395.1  599.06   405.1  598.75   415.1  599.75   435.5  604.57   445.6  606.07
   455.7   611.1   465.9  619.65     476  626.64   506.4  640.01   526.6   648.4
   546.9  656.08   577.3  665.85   607.7  676.38     638     689   698.8  715.78
   759.6  740.02   779.8  747.73     790  751.12   800.1  753.84   820.3  758.06
#Mann= 3 , 0 , 0
    10.1     .08       0   395.1    .045       0   415.1     .08       0
#XS Ineff= 2 , 0
          332.54  632.05
Permanent Ineff=
       F       F
Bank Sta=395.1,415.1
XS Rating Curve= 0 ,0
Exp/Cntr=0.3,0.1

Type RM Length L Ch R = 1 ,3037.1  ,391.8,371.3,351.5
XS GIS Cut Line= 5
     1520174.806      407087.003     1519882.878      407064.042
     1519722.541      407034.684     1519648.337      406978.735
     1519397.049      407011.159
#Sta/Elev= 30
       0  673.99    10.1  673.99   111.1  640.39   141.4  630.92   161.6  624.98
   191.9  616.74     212  611.72   242.3  605.39   262.5  601.73   272.6  600.36
   282.7  599.71   369.5  598.85   398.3  597.69   417.1  595.99   427.1  595.25
   437.1  595.73   455.8   598.9   465.1  599.65   502.3  599.41   530.2  602.26
   548.8  603.49     569  607.17   579.2  609.57   589.3  612.39     640  627.57
   660.2  634.01   710.9  650.97   731.2  657.22   771.7  667.72   802.1  677.23
#Mann= 3 , 0 , 0
       0     .08       0   417.1    .045       0   437.1     .08       0
#XS Ineff= 2 , 0
                          463.55          603.67
Permanent Ineff=
       F       F
Bank Sta=417.1,437.1
XS Rating Curve= 0 ,0
Exp/Cntr=0.3,0.1

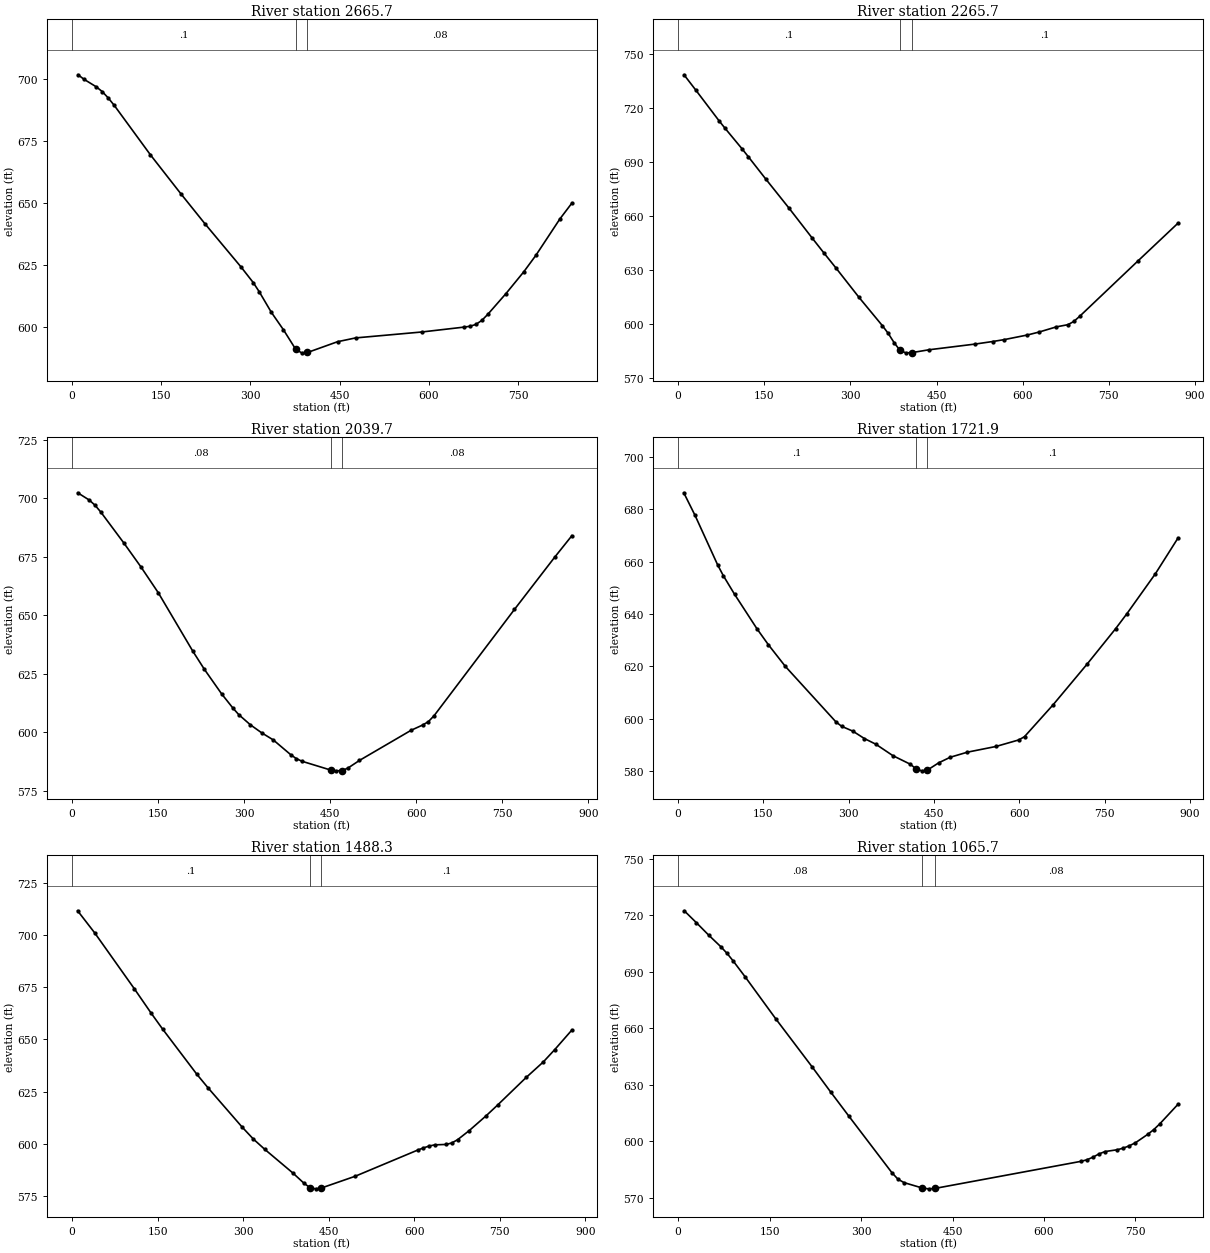
Type RM Length L Ch R = 1 ,2665.7  ,416.5,400,383.1
XS GIS Cut Line= 3
       1520143.6      406465.817     1519829.917      406690.599
     1519443.344      406929.558
#Sta/Elev= 30
    10.2  701.84    20.3  700.01    40.6  697.01    50.8  695.07    60.9  692.49
    71.1  689.47     132  669.46   182.8  653.84   223.4  641.69   284.4  624.13
   304.7  617.89   314.8  614.18   335.1  605.89   355.4  598.85   375.9  591.01
   385.9   589.5   395.9  589.64   446.5     594   476.8  595.53   587.9  597.92
   658.6  599.88   668.7  600.22   678.8  600.96   688.9  602.59     699  605.05
   729.3  613.37   759.6  622.27   779.8  628.88   820.2   643.6   840.4     650
#Mann= 3 , 0 , 0
       0      .1       0   375.9    .045       0   395.9     .08       0
Bank Sta=375.9,395.9
XS Rating Curve= 0 ,0
Exp/Cntr=0.3,0.1

Type RM Length L Ch R = 1 ,2265.7  ,223.7,226,227
XS GIS Cut Line= 3
     1519636.974      406063.779     1519522.967       406443.31
     1519364.622      406890.197
#Sta/Elev= 30
    10.2  738.66    30.5  730.23    71.1  713.11    81.3  709.03   111.8  697.25
   121.9  693.18   152.4  680.71   193.1  664.43   233.7  647.67     254  639.43
   274.4   631.3     315  614.76   355.6  599.05   365.8  594.74     376  589.62
   386.3  585.29   396.3  583.94   406.3  584.03   436.6  585.64   517.3  588.83
   547.6  590.24   567.8   591.3   608.1  593.87   628.3   595.5   658.6   598.4
   678.7  599.61   688.8  601.39   698.9  604.21   799.8  634.85   870.4  656.13
#Mann= 3 , 0 , 0
       0      .1       0   386.3    .045       0   406.3      .1       0
Bank Sta=386.3,406.3
XS Rating Curve= 0 ,0
Exp/Cntr=0.3,0.1

Type RM Length L Ch R = 1 ,2039.7  ,299.6,317.8,335.9
XS GIS Cut Line= 3
     1519453.185       406001.29     1519374.462      406260.417
     1519151.415      406818.034
#Sta/Elev= 30
      10   702.4    30.1  699.29    40.1  697.09    50.2  694.17    90.3  680.95
   120.4  670.61   150.5   659.6   210.6  634.63   230.7  626.89   260.8  616.37
   280.8  610.19   290.8  607.45   310.9  603.13   330.9  599.65   350.9  596.65
   380.9  590.41   390.9  588.67   400.9  587.52     451  583.75     461  583.42
     471  583.54     481   584.6     501  587.86   591.1  600.77   611.1  603.01
   621.2  604.46   631.2  607.02   771.3   652.5   841.4  674.84   871.4  684.05
#Mann= 3 , 0 , 0
       0     .08       0     451    .045       0     471     .08       0
Bank Sta=451,471
XS Rating Curve= 0 ,0
Exp/Cntr=0.3,0.1

Type RM Length L Ch R = 1 ,1721.9  ,257.8,233.6,209.3
XS GIS Cut Line= 4
      1519305.58      405961.928     1519151.415      406227.616
     1518916.499      406364.188     1518852.926       406657.31
#Sta/Elev= 30
     9.9  686.32    29.7  677.69    69.4  658.81    79.3  654.71    99.1  647.59
   138.7  634.35   158.5  628.34   188.3  620.07   277.4  598.84   287.4  597.16
   307.2   595.3   327.3   592.5   347.4  590.34   377.6  585.94   407.8  582.72
   417.9     581   427.9  580.16   437.9  580.41   458.1  583.23   478.3  585.35
   508.5  587.29   558.8  589.47   598.9  591.97   608.9  593.23   658.9  605.32
   718.9  620.91   768.9   634.4   788.9  640.17   838.9   655.4   878.8  669.09
#Mann= 3 , 0 , 0
       0      .1       0   417.9    .045       0   437.9      .1       0
Bank Sta=417.9,437.9
XS Rating Curve= 0 ,0
Exp/Cntr=0.3,0.1

Type RM Length L Ch R = 1 ,1488.3  ,404.1,422.6,443.3
XS GIS Cut Line= 4
     1518954.131      405753.114       1518909.5      405967.291
     1518872.607       406332.58      1518703.76      406569.161
#Sta/Elev= 30
     9.9  711.51    39.8  700.95   109.4  674.16   139.2  662.37   159.1  654.82
   218.8  633.31   238.6  626.76   298.2  608.03     318  602.26   337.9  597.36
   387.5  585.96   407.3  580.98   417.2  579.04   427.2  578.42   437.2  578.81
   496.6  584.44     606  596.95     616  597.97     626  598.89     636  599.47
   656.1  599.67   666.1   600.4   676.1  601.93   696.2  606.22   726.2  613.39
   746.3  618.52   796.4  631.73   826.5  639.17   846.5  645.06   876.6  654.44
#Mann= 3 , 0 , 0
       0      .1       0   417.2    .045       0   437.2      .1       0
Bank Sta=417.2,437.2
XS Rating Curve= 0 ,0
Exp/Cntr=0.3,0.1

Type RM Length L Ch R = 1 ,1065.7  ,416.5,400,382
XS GIS Cut Line= 3
     1518859.991      405689.657      1518552.42      405961.625
     1518225.366      406207.738
#Sta/Elev= 30
      10  722.37      30  716.02    50.1  709.44    70.1  703.25    80.1   699.8
    90.1  695.78   110.2  687.16   160.2  664.95   220.3  639.24   250.3  626.07
   280.4  613.13   350.5  583.32   360.5  579.84   370.5  578.01   400.6  575.13
   410.6  574.71   420.6   574.9   660.1  589.28   670.1  590.11   680.1  591.49
   690.1  593.23   700.1  594.51     720  595.46     730  596.32     740  597.58
     750  599.18     770  603.62   779.9  606.13   789.9  609.21   819.9  619.66
#Mann= 3 , 0 , 0
       0     .08       0   400.6    .045       0   420.6     .08       0
Bank Sta=400.6,420.6
XS Rating Curve= 0 ,0
Exp/Cntr=0.3,0.1

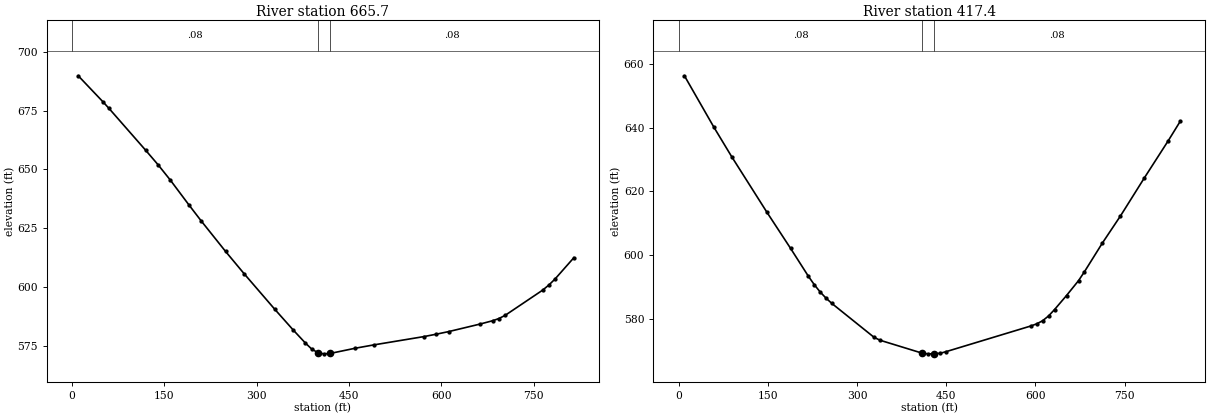
Type RM Length L Ch R = 1 ,665.7   ,249.4,248.3,246.8
XS GIS Cut Line= 3
     1518323.417      405323.458     1518247.199      405725.185
     1518164.106      406122.653
#Sta/Elev= 30
      10  689.91    49.9   678.9    59.8  676.06   119.7  658.13   139.6  652.03
   159.6  645.47   189.5     635   209.4  628.19   249.3  615.08   279.2  605.66
   329.1  590.47     359  581.66     379  576.04   388.9  573.57   398.9  571.98
   408.9  571.45   418.9   571.6   459.7  573.83   490.1  575.26   571.3  578.79
   591.6  579.82   611.9  580.94   662.7  584.14     683  585.55   693.1  586.47
   703.3  587.83   764.2  598.57   774.3  600.74   784.5  603.35     815  612.41
#Mann= 3 , 0 , 0
       0     .08       0   398.9    .045       0   418.9     .08       0
Bank Sta=398.9,418.9
XS Rating Curve= 0 ,0
Exp/Cntr=0.3,0.1

Type RM Length L Ch R = 1 ,417.4   ,406.7,417.4,428
XS GIS Cut Line= 4
     1518070.347      405243.268     1518031.124      405498.215
     1517985.364      405808.729     1517965.753      406080.019
#Sta/Elev= 30
     9.9  656.26    59.5  640.12    89.3  630.92   148.8  613.42   188.5  602.12
   218.3  593.42   228.2  590.78   238.1  588.49     248  586.55   257.9  584.87
   328.8  574.26   338.9  573.34   409.9  569.28   419.9  569.08   429.9  569.09
   440.2  569.26   450.3  569.79     592  577.79     602  578.46   612.1  579.44
   622.2  580.95   632.3  582.97   652.4  587.36   672.6  592.02   682.6  594.83
   712.9  603.87   743.1   612.3   783.4  624.27   823.7  635.96   843.8  642.03
#Mann= 3 , 0 , 0
       0     .08       0   409.9    .045       0   429.9     .08       0
Bank Sta=409.9,429.9
XS Rating Curve= 0 ,0
Exp/Cntr=0.3,0.1

Chan Stop Cuts=-1
Use User Specified Reach Order=0